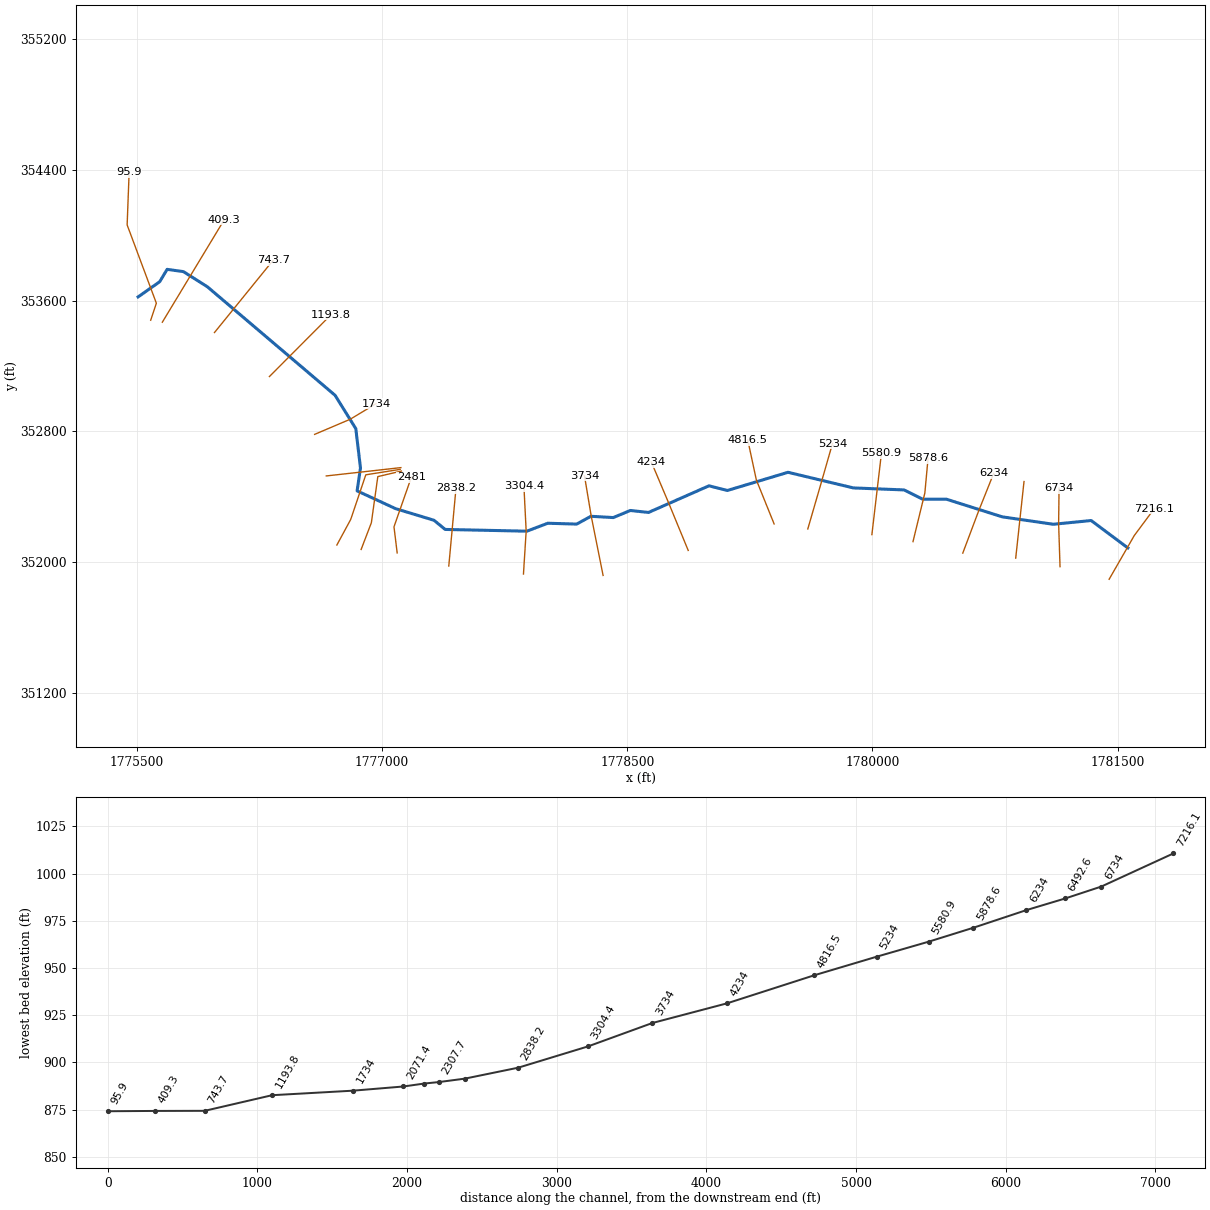
--- BROWNSBR.prj (project) ---

Proj Title=BROWNSBR
Current Plan=p01
Default Exp/Contr=0,0
English Units
Geom File=g01
Flow File=f01
Plan File=p01
Background Map Layer=FpSmooth_P100yr
BEGIN DESCRIPTION:
END DESCRIPTION:
DSS Export Rating Curves= 0
DSS Export Rating Curve Sorted= 0
DSS Export Volume Flow Curves= 0
DXF OffsetX= 0
DXF OffsetY= 0
DXF ScaleX= 0
DXF ScaleY= 0

--- BROWNSBR.p01 (plan) ---

Plan Title=Floodplain
Program Version=4.00
Geom File=g01
Flow File=f01
K Sum by GR=0
Std Step Tol=0.01
Critical Tol=0.01
Num of Std Step Trials=20
Max Error Tol=0.3
Flow Tol Ratio=0.001
Split Flow NTrial=30
Split Flow Tol=0.02
Split Flow Ratio=0.02
Log Output Level=0
Friction Slope Method=1
Unsteady Friction Slope Method=2
Unsteady Bridges Friction Slope Method=1
Global Log Level=0
CheckData=False
Run HTab=0
Run UNet=0
Run PostProcess=0
UNET Theta=0
UNET Theta Warmup=0
UNET ZTol=0
UNET ZSATol=0
UNET MxIter=0
UNET MaxInSteps=0
UNET DtIC=0
UNET DtMin=0
UNET MaxCRTS=0
UNET WFStab=0
UNET SFStab=0
UNET WFX=0
UNET SFX=0
UNET DSS MLevel=0
UNET DZMax Abort=0
UNET Convert EG Bridges=0
UNET Use Existing IB Tables=0
UNET Froude Limit=0
UNET Froude Power=0
Write IC File=0
Echo Input=False
Echo Output=False
Write Detailed=0

--- BROWNSBR.f01 (steady flow) ---

Flow Title=NFF Regression Equation
Program Version=5.03
Number of Profiles= 1
Profile Names=P100yr
River Rch & RM=BROWNSBR,Main            ,7216.1
871.7785
River Rch & RM=BROWNSBR,Main            ,6734
1112.988
River Rch & RM=BROWNSBR,Main            ,1193.8
1228.179
Boundary for River Rch & Prof#=BROWNSBR,Main            , 1
Up Type= 0
Dn Type= 3
Dn Slope=0.00764
DSS Import GetInterval= 0
DSS Import GetPeak= 0
DSS Import FillOption= 0

--- BROWNSBR.g01 (geometry) ---

Geom Title=USGS 10m DEM
Program Version=5.03

River Reach=BROWNSBR        ,Main
Reach XY= 30
     1781562.611      352087.432     1781338.218      352254.967
     1781106.816      352232.042     1780794.203      352277.476
     1780453.109      352385.297     1780307.991      352385.297
     1780193.389      352442.259     1779883.488      352454.465
     1779483.398       352550.08     1779112.467      352438.868
     1778999.899      352467.349     1778629.714      352304.306
     1778518.602      352316.459     1778414.436      352273.056
     1778277.283      352280.869     1778190.478      352233.126
     1778013.394      352238.334      1777885.79      352189.723
     1777385.962        352200.4     1777317.214      352256.563
     1777081.971      352327.744     1776846.932        352436.4
     1776867.561      352576.876     1776838.915      352817.327
     1776712.179      353021.233     1775930.929      353685.296
     1775784.227      353778.178     1775684.401      353792.066
     1775639.262      353716.546     1775506.952      353623.414

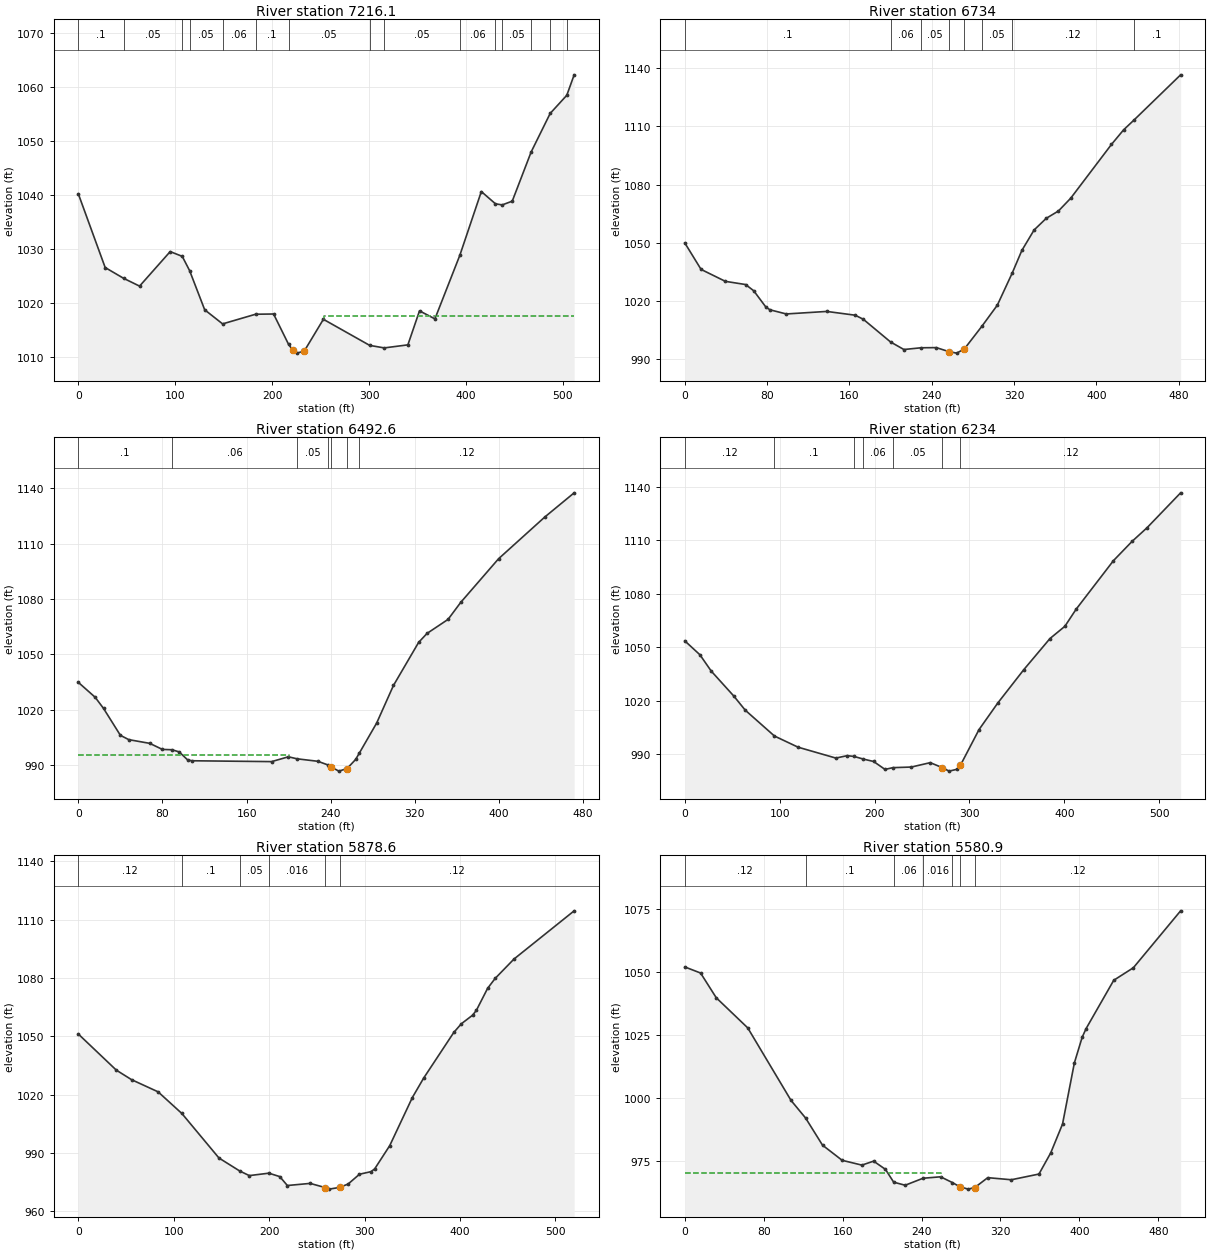
Type RM Length L Ch R = 1 ,7216.1  ,469.2,482,493.7
XS GIS Cut Line= 3
     1781448.178      351895.409     1781601.723      352162.616
     1781723.142      352325.954
#Sta/Elev= 30
       0 1040.18    27.7 1026.55    46.71024.556    63.2 1023.11    94.8  1029.5
  107.241028.617  114.831025.981   130.4 1018.73  148.891016.121  182.961017.908
   201.5 1017.95  217.021012.318   221.3 1011.26   225.2 1010.71   233.1 1011.07
   252.9 1016.97   300.71012.141   315.71011.676   340.1 1012.24   352.1 1018.53
     368 1017.05  393.711028.811   415.9 1040.61  430.511038.338  437.44 1038.14
   447.8 1038.83  467.311047.935  486.951055.067  504.111058.428   511.7 1062.21
#Mann= 15 ,-1 , 0
       0      .1       0    46.7     .05       0  107.24      .1       0
  114.83     .05       0  148.89     .06       0  182.96      .1       0
  217.02     .05       0   300.7    .045       0   315.7     .05       0
  393.71     .06       0  430.51    .016       0  437.44     .05       0
  467.31    .016       0  486.95     .05       0  504.11    .016       0
#XS Ineff= 2 , 0
                          253.28         1017.62
Permanent Ineff=
       F       F
Bank Sta=221.3,233.1
XS Rating Curve= 0 ,0
Exp/Cntr=0.3,0.1

Type RM Length L Ch R = 1 ,6734    ,244.4,241.4,239.1
XS GIS Cut Line= 3
     1781147.799      351972.347     1781139.161      352236.355
     1781141.922      352454.019
#Sta/Elev= 30
       0 1049.95    15.8 1036.31    39.4 1030.15    59.1  1028.5      67 1025.28
    78.8 1016.88    82.8 1015.47    98.6 1013.34     138 1014.64   165.6 1012.69
   173.5 1010.59  199.96998.8931   212.9  995.01  229.51 995.907   244.4  995.99
   256.6  993.93   264.2  993.15   271.6  995.28   288.61006.933   303.7 1017.88
  318.141034.397   327.5 1046.05   339.4 1056.61   351.2 1062.62   363.1 1066.42
     375    1073   414.6 1100.72   426.4 1108.24   436.3 1113.19   481.8 1136.59
#Mann= 8 ,-1 , 0
       0      .1       0  199.96     .06       0  229.51     .05       0
   256.6    .045       0   271.6      .1       0   288.6     .05       0
  318.14     .12       0   436.3      .1       0
Bank Sta=256.6,271.6
XS Rating Curve= 0 ,0
Exp/Cntr=0.3,0.1

Type RM Length L Ch R = 1 ,6492.6  ,264.2,258.6,252.3
XS GIS Cut Line= 2
     1780876.586      352024.599     1780927.367      352493.349
#Sta/Elev= 30
       0  1034.9      16 1026.83      24 1020.76      40 1006.22      48 1003.88
    67.9 1001.88    79.9   998.6   89.05998.4127    95.9  997.25   103.9  992.94
   107.9  992.45   183.8  991.99   199.8   994.6  207.89993.5197   227.8  992.16
   237.6990.1361   240.5  989.11   247.7  986.84   255.5  988.21   263.7  993.16
  267.31996.6978   283.7 1012.88   299.7 1033.26   323.6 1056.53   331.6  1061.4
   351.6    1069   363.6 1078.17   399.6 1101.81   443.5 1124.37   471.5 1137.51
#Mann= 7 ,-1 , 0
       0      .1       0   89.05     .06       0  207.89     .05       0
   237.6      .1       0   240.5    .045       0   255.5      .1       0
  267.31     .12       0
#XS Ineff= 2 , 0
          200.29  995.31
Permanent Ineff=
       F       F
Bank Sta=240.5,255.5
XS Rating Curve= 0 ,0
Exp/Cntr=0.3,0.1

Type RM Length L Ch R = 1 ,6234    ,352.2,355.4,358.2
XS GIS Cut Line= 3
     1780552.713      352055.456     1780650.856      352316.217
     1780741.485      352542.777
#Sta/Elev= 30
       0 1053.61    15.9 1045.85    27.9 1036.67    51.7 1022.69    63.7 1014.82
   94.481000.344   119.4  994.09   159.2     988   171.2  989.35  178.33988.9136
  187.88  987.48     199  986.09     211  981.66  219.43982.6365   238.8  982.98
   258.7  985.43   271.1  982.72   278.6  980.69   286.5  981.67   290.4  983.86
   310.1 1003.93   329.8 1018.76   357.3 1037.49   384.9 1054.92   400.6 1061.77
   412.4 1071.29   451.8 1098.52   471.5 1109.34   487.2 1116.94   522.6 1136.49
#Mann= 7 ,-1 , 0
       0     .12       0   94.48      .1       0  178.33     .05       0
  187.88     .06       0  219.43     .05       0   271.1    .045       0
   290.4     .12       0
Bank Sta=271.1,290.4
XS Rating Curve= 0 ,0
Exp/Cntr=0.3,0.1

Type RM Length L Ch R = 1 ,5878.6  ,294.9,297.7,300.5
XS GIS Cut Line= 3
     1780248.137      352125.865     1780320.686      352423.841
      1780340.33      352635.985
#Sta/Elev= 30
       0  1051.1    39.8 1032.54    55.8 1027.63    83.6 1021.37  108.521010.237
   147.4  987.33  169.31980.6027   179.2  978.28  199.71979.5271   211.1  977.77
   219.1  973.18     243  974.27   258.8  972.11   262.9  971.32   273.8   972.2
   282.8  973.95   294.7  978.99   306.7   980.3   310.6  981.72   326.4   993.7
   350.1 1018.44   361.9  1028.4   393.5  1051.9   401.4 1056.36   413.2 1060.79
   417.2 1063.29     429 1074.63   436.9 1079.72   456.6 1089.67   519.7 1114.49
#Mann= 6 ,-1 , 0
       0     .12       0  108.52      .1       0  169.31     .05       0
  199.71    .016       0   258.8    .045       0   273.8     .12       0
Bank Sta=258.8,273.8
XS Rating Curve= 0 ,0
Exp/Cntr=0.3,0.1

Type RM Length L Ch R = 1 ,5580.9  ,350.4,346.8,343.1
XS GIS Cut Line= 2
     1779996.595      352168.696     1780055.188      352667.828
#Sta/Elev= 30
       0 1051.94      16 1049.53    31.9 1039.73    63.8 1027.81   107.7  999.08
  122.52992.0754   139.6  981.37   159.5  975.37   179.5  973.47   191.4  975.04
   203.4  971.79  211.74966.7073   223.4   965.5  241.48968.2673   259.3  968.84
  271.22966.5557   278.9  964.89   287.2  963.96   293.9  964.58   307.1   968.5
     331  967.67     359  969.93   370.9  978.29   382.9  989.73   394.9 1013.95
   402.8 1024.09   406.8 1027.54   434.8 1046.66   454.7 1051.62   502.6 1074.16
#Mann= 7 ,-1 , 0
       0     .12       0  122.52      .1       0  211.74     .06       0
  241.48    .016       0  271.22     .12       0   278.9    .045       0
   293.9     .12       0
#XS Ineff= 2 , 0
          259.75  970.31
Permanent Ineff=
       F       F
Bank Sta=278.9,293.9
XS Rating Curve= 0 ,0
Exp/Cntr=0.3,0.1

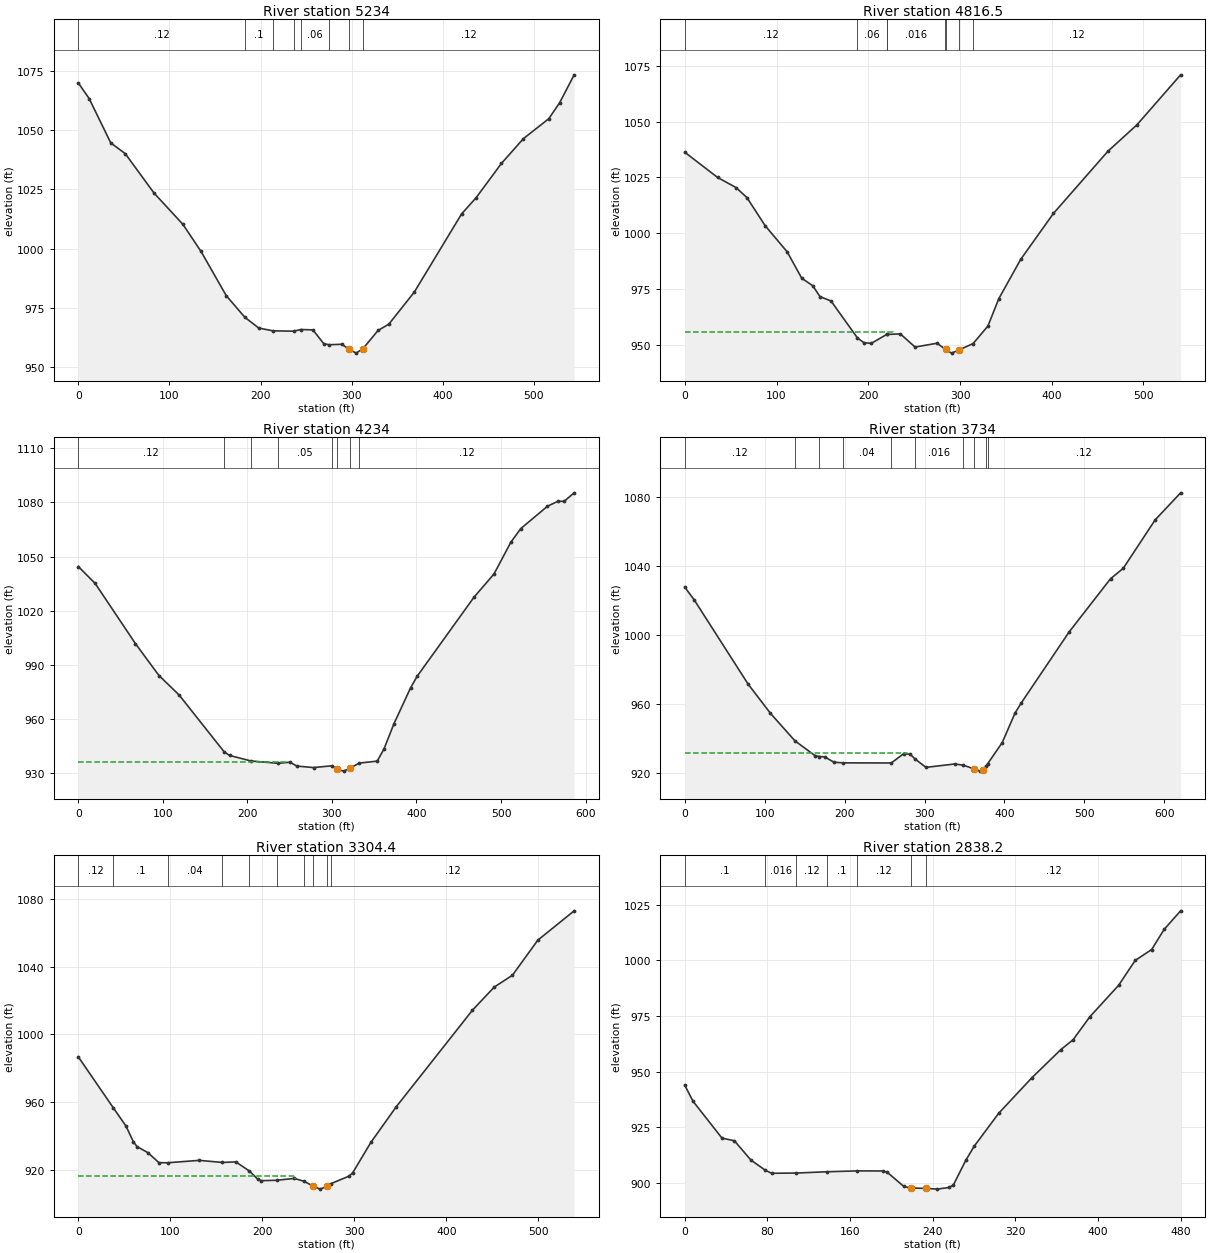
Type RM Length L Ch R = 1 ,5234    ,402.6,417.5,428.4
XS GIS Cut Line= 3
     1779604.522      352203.431     1779689.569       352496.37
     1779755.588      352726.327
#Sta/Elev= 30
       0 1069.77    11.9 1063.17    35.6 1044.53    51.5    1040    83.2 1023.36
   114.9 1010.19   134.7  998.82   162.4   980.2  182.82971.1037   198.1  966.57
  213.58965.4091  236.22965.2593  244.33965.9503   257.5  965.81   269.4  960.02
  275.09959.5485   289.2  959.75   297.5  957.57     305  956.02   312.5  957.92
     329  965.55   340.9  968.23   368.8  981.71   420.7 1014.61   436.6 1021.41
   464.5  1035.9   488.5 1046.28   516.4  1054.7   528.3 1061.39   544.3 1073.18
#Mann= 8 ,-1 , 0
       0     .12       0  182.82      .1       0  213.58     .05       0
  236.22     .04       0  244.33     .06       0  275.09    .016       0
   297.5    .045       0   312.5     .12       0
Bank Sta=297.5,312.5
XS Rating Curve= 0 ,0
Exp/Cntr=0.3,0.1

Type RM Length L Ch R = 1 ,4816.5  ,581.6,582.5,586.4
XS GIS Cut Line= 3
     1779398.424      352234.062     1779289.522      352503.726
     1779237.147      352747.838
#Sta/Elev= 30
       0 1036.31    35.8    1025    55.8 1020.48    67.7 1015.99    87.6 1003.36
   111.6  991.63   127.5  979.77   139.4  976.45   147.4  971.52   159.4  969.57
  188.18953.0023   195.2  950.85   203.2  950.54  220.03954.5392  220.25954.5651
     235  954.79     251   948.9   274.9   950.6  283.74 948.002   284.3  947.81
   290.8  946.17   299.3  947.65  314.32950.4786   330.4   958.3   342.3  970.61
   366.1   988.2   401.8 1008.83   461.2 1036.75   492.9 1048.64   540.5 1071.06
#Mann= 8 ,-1 , 0
       0     .12       0  188.18     .06       0  220.03     .05       0
  220.25    .016       0  283.74      .1       0   284.3    .045       0
   299.3      .1       0  314.32     .12       0
#XS Ineff= 2 , 0
          227.42  955.59
Permanent Ineff=
       F       F
Bank Sta=284.3,299.3
XS Rating Curve= 0 ,0
Exp/Cntr=0.3,0.1

Type RM Length L Ch R = 1 ,4234    ,504.2,500,494.6
XS GIS Cut Line= 3
     1778872.789      352071.973     1778753.144      352362.306
     1778647.134      352613.342
#Sta/Elev= 30
       0 1044.47    19.9 1035.13    67.6 1001.81    95.4  984.17   119.2  973.44
  172.38942.0409   178.9  939.99  204.33936.9218  236.27  935.65   250.4  936.25
   258.4  934.12   278.2  933.28  300.17934.2691   306.5  932.24     314  931.31
   321.5  932.95  332.18935.7402   353.5  936.85   361.4   943.4   373.3  957.48
     393  977.37   400.9  983.85     468 1027.49   491.7 1040.36   511.5 1057.82
   523.3 1065.43   554.9  1077.8   566.8 1080.45   574.7 1080.57   586.5 1085.23
#Mann= 8 ,-1 , 0
       0     .12       0  172.38      .1       0  204.33    .016       0
  236.27     .05       0  300.17     .06       0   306.5    .045       0
   321.5     .06       0  332.18     .12       0
#XS Ineff= 2 , 0
          247.33  936.53
Permanent Ineff=
       F       F
Bank Sta=306.5,321.5
XS Rating Curve= 0 ,0
Exp/Cntr=0.3,0.1

Type RM Length L Ch R = 1 ,3734    ,435.9,429.6,426
XS GIS Cut Line= 3
     1778351.997       351918.99     1778279.509      352281.172
     1778238.054      352528.705
#Sta/Elev= 30
       0 1027.74    11.9 1020.25    79.4   971.3   107.2  954.44  137.84938.4561
   162.8  929.92  167.96929.3381   174.8   929.2   186.7  926.04  198.09925.6738
  258.33 925.601     274  931.05     282  930.63  288.45927.8116   301.8  923.05
   337.6  925.02   348.7 924.312   361.9  922.14   369.4  920.87   373.4  921.64
   376.9  923.78  378.76925.0265   397.2  937.47   413.2  954.59   421.2  960.64
   480.9 1001.74   532.7 1032.64   548.6 1038.68   588.5 1066.81   620.4 1082.54
#Mann= 10 ,-1 , 0
       0     .12       0  137.84      .1       0  167.96     .06       0
  198.09     .04       0  258.33     .05       0  288.45    .016       0
   348.7      .1       0   361.9    .045       0   376.9      .1       0
  378.76     .12       0
#XS Ineff= 2 , 0
          277.67  931.25
Permanent Ineff=
       F       F
Bank Sta=361.9,373.4
XS Rating Curve= 0 ,0
Exp/Cntr=0.3,0.1

Type RM Length L Ch R = 1 ,3304.4  ,466.6,466.2,463
XS GIS Cut Line= 3
     1777864.774      351927.659     1777881.332      352189.858
     1777867.499      352465.549
#Sta/Elev= 30
       0  986.67   37.98956.5796    51.8  945.74    59.7  936.62    63.7  933.67
    75.6  930.04    87.6  924.12   97.16924.0732   131.4  925.49  156.35 924.266
   171.2  924.57  185.95 919.152     195  914.37     199  913.47  215.54 913.732
   234.9  914.81  245.14913.1301   254.9  910.33   262.7  908.48   269.9  910.04
  274.73911.7633   294.3   916.2   298.2  918.19   317.9  936.11   345.5  957.21
   428.3 1014.29     452 1027.95   471.7 1034.93   499.3 1055.67   538.8 1073.02
#Mann= 10 ,-1 , 0
       0     .12       0   37.98      .1       0   97.16     .04       0
  156.35      .1       0  185.95     .06       0  215.54    .016       0
  245.14     .05       0   254.9    .045       0   269.9     .05       0
  274.73     .12       0
#XS Ineff= 2 , 0
          235.65  916.52
Permanent Ineff=
       F       F
Bank Sta=254.9,269.9
XS Rating Curve= 0 ,0
Exp/Cntr=0.3,0.1

Type RM Length L Ch R = 1 ,2838.2  ,361.9,357.2,351.9
XS GIS Cut Line= 2
     1777407.836      351976.422     1777452.107      352454.286
#Sta/Elev= 30
       0  943.85       8  936.66      36  920.12      48  918.93      64  910.26
   78.09905.6464      84  904.33  107.76904.4306  137.42905.0122  167.08905.4023
     192  905.36     196  904.76     212  898.41   218.7   897.7   233.7  897.55
     244  897.21     256  897.96     260  899.13     272  910.17     280  916.42
   303.9  931.32   335.9  947.22   363.9  959.84   375.9  964.33   391.9  974.55
   419.9  988.76   435.9  999.92   451.9 1004.83   463.9 1013.84   479.9  1022.2
#Mann= 7 ,-1 , 0
       0      .1       0   78.09    .016       0  107.76     .12       0
  137.42      .1       0  167.08     .12       0   218.7    .045       0
   233.7     .12       0
Bank Sta=218.7,233.7
XS Rating Curve= 0 ,0
Exp/Cntr=0.3,0.1

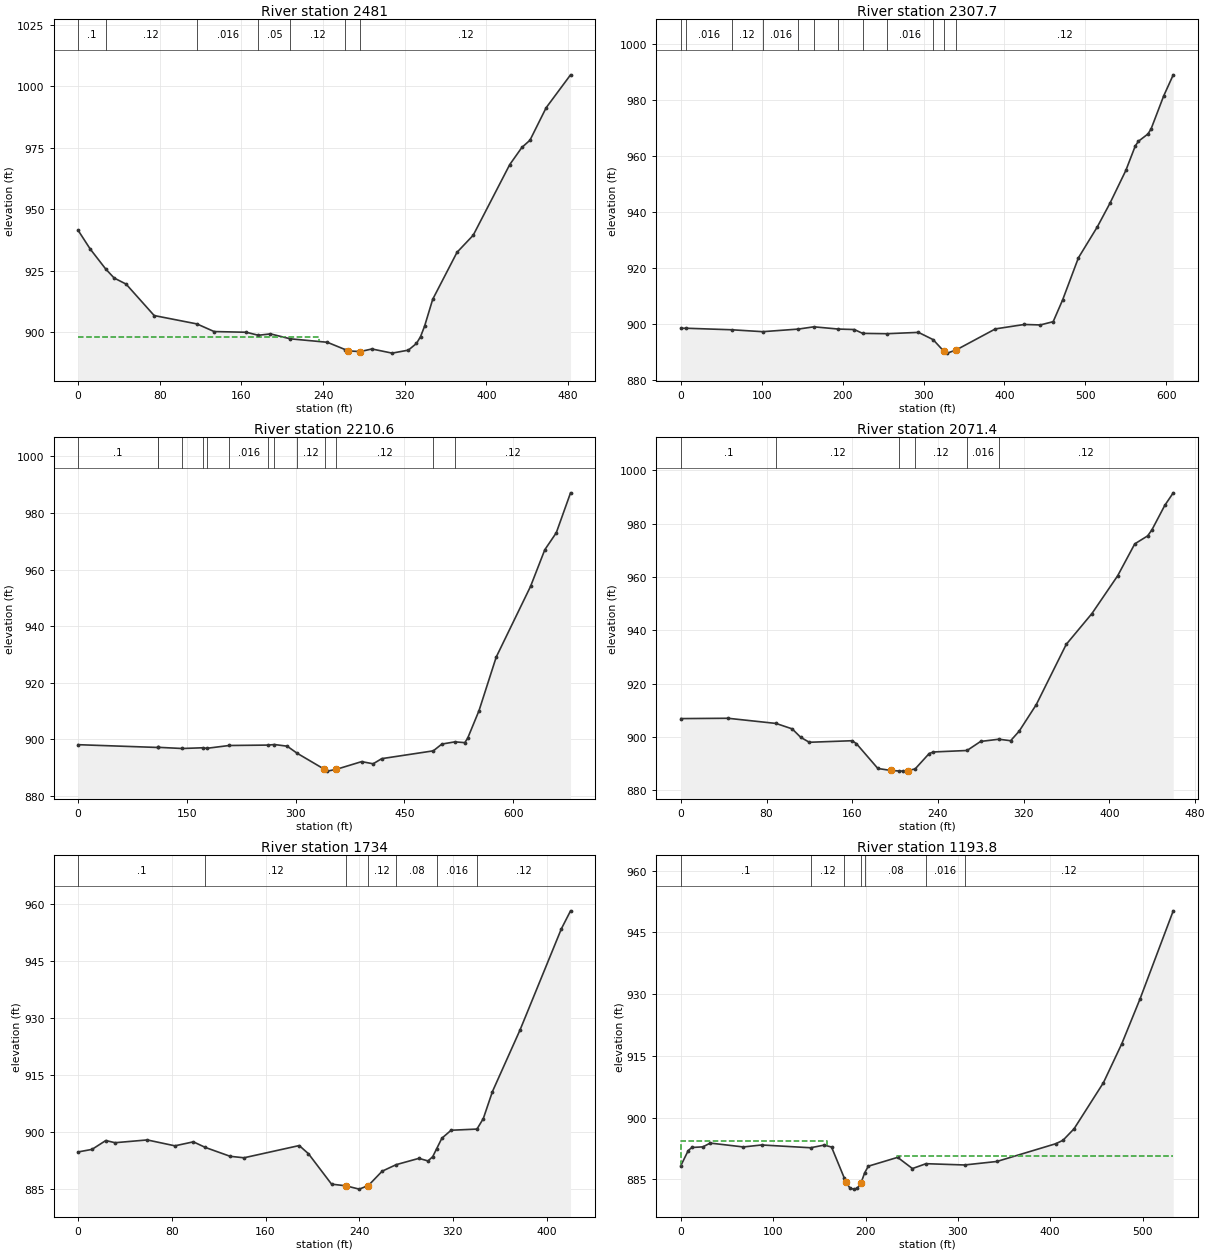
Type RM Length L Ch R = 1 ,2481    ,168.9,173.4,177.9
XS GIS Cut Line= 3
     1777092.081      352056.825     1777072.549      352216.331
     1777178.886       352520.15
#Sta/Elev= 30
       0  941.37    11.8  933.79   27.11925.5924    35.3  921.97      47   919.5
    74.5   906.7  116.38903.2925   133.3  900.18   164.7   899.9  176.67898.6726
   188.5  899.23  207.97 897.223   244.2  895.82   261.6  892.86     264  892.31
   276.6  892.04   287.9  893.09   307.7   891.4   323.6  892.61   331.6  895.35
   335.6  898.14   339.5  902.34   347.5  913.32   371.3  932.43   387.2   939.4
     423  968.16   434.9  975.15   442.8  978.07   458.7  991.32   482.6  1004.7
#Mann= 7 ,-1 , 0
       0      .1       0   27.11     .12       0  116.38    .016       0
  176.67     .05       0  207.97     .12       0   261.6    .045       0
   276.6     .12       0
#XS Ineff= 2 , 0
          235.58  897.84
Permanent Ineff=
       F       F
Bank Sta=264,276.6
XS Rating Curve= 0 ,0
Exp/Cntr=0.3,0.1

Type RM Length L Ch R = 1 ,2307.7  ,101.3,97.1,92.9
XS GIS Cut Line= 4
     1776871.552      352077.883     1776934.052      352241.078
     1776973.635      352523.717     1777118.079      352557.744
#Sta/Elev= 30
       0  898.45    6.27898.4958    62.7897.9443  101.15897.2606  145.29 898.194
  164.41899.0012  194.82898.1943   214.4  898.03  224.65896.6603  254.47896.5377
   293.7  897.01  311.79894.4231   325.2  890.22   329.3  889.59   340.2  890.71
   388.8  898.26   424.5  899.84   444.3  899.67   460.2  900.84   471.9  908.64
   491.4  923.69   514.8  934.77   530.4  943.22     550  954.93   561.7  963.71
   565.6  965.37   577.3  967.97   581.2  969.78   596.8   981.6   608.6  989.13
#Mann= 12 ,-1 , 0
       0     .12       0    6.27    .016       0    62.7     .12       0
  101.15    .016       0  145.29      .1       0  164.41     .06       0
  194.82    .016       0  224.65      .1       0  254.47    .016       0
  311.79     .12       0   325.2    .045       0   340.2     .12       0
Bank Sta=325.2,340.2
XS Rating Curve= 0 ,0
Exp/Cntr=0.3,0.1

Type RM Length L Ch R = 1 ,2210.6  ,166.1,139.2,112.3
XS GIS Cut Line= 4
     1776723.165      352105.256       1776807.8      352261.506
     1776900.074      352534.726     1777110.491      352568.059
#Sta/Elev= 30
       0  898.15  109.89897.1685  110.59897.2192  143.48896.8043   172.6 897.066
  177.07896.8575  208.29897.8667  262.43898.0135  270.64898.2083   288.3  897.62
  301.82895.1598   339.7  889.45   340.9  889.25   343.6  888.81   355.5  889.41
   355.9  889.43     391  892.17   406.8   891.4   418.7  893.22  489.83895.9769
   501.6  898.37  519.73899.1577   533.2  898.87   537.1  900.38   552.9  910.22
   576.6  929.12   623.9  954.06   643.6  967.03   659.4  973.01   679.1  987.13
#Mann= 14 ,-1 , 0
       0      .1       0  109.89     .12       0  110.59     .06       0
  143.48      .1       0   172.6     .06       0  177.07     .08       0
  208.29    .016       0  262.43     .06       0  270.64      .1       0
  301.82     .12       0   340.9    .045       0   355.9     .12       0
  489.83    .016       0  519.73     .12       0
Bank Sta=339.7,355.5
XS Rating Curve= 0 ,0
Exp/Cntr=0.3,0.1

Type RM Length L Ch R = 1 ,2071.4  ,330.7,337.4,347.2
XS GIS Cut Line= 2
     1776658.053      352527.745     1777114.867      352578.744
#Sta/Elev= 30
       0  906.93      44  907.05   88.81905.1144   103.9  903.08   111.9  899.91
   119.9  898.06   159.9  898.64   163.9  897.53   183.9  888.24   195.8  887.52
   203.7   887.3   207.8  887.25   211.8  887.43   218.7  888.08   231.8  893.85
   235.8  894.43  267.12894.9805   279.8  898.37  296.84899.2026   307.8  898.64
   315.8  902.23   331.8   912.2   359.7  934.72   383.7  946.28   407.7  960.42
   423.7  972.39   435.7  975.37   439.7  977.64   451.7   986.8   459.6   991.5
#Mann= 6 ,-1 , 0
       0      .1       0   88.81     .12       0   203.7    .045       0
   218.7     .12       0  267.12    .016       0  296.84     .12       0
Bank Sta=195.8,211.8
XS Rating Curve= 0 ,0
Exp/Cntr=0.3,0.1

Type RM Length L Ch R = 1 ,1734    ,531.4,540.2,545.6
XS GIS Cut Line= 3
     1776587.211      352782.271     1776804.431      352874.638
     1776962.518      352969.759
#Sta/Elev= 30
       0  894.82    11.8  895.49    23.6  897.82    31.5  897.25      59  897.98
    82.6  896.43    98.4  897.48  108.71895.9905   129.8  893.67   141.6  893.28
   188.8   896.5   196.7  894.34   216.4  886.34   228.5  885.91     240  885.03
   247.8  885.97   259.6  889.75  271.64891.4772     291  893.13   298.8  892.45
   302.8  893.58  306.11895.6339   310.6  898.43   318.5  900.53  340.58900.8388
     346  903.61   353.8  910.72   377.4  926.96   412.7  953.59   420.5  958.29
#Mann= 7 ,-1 , 0
       0      .1       0  108.71     .12       0   228.5    .045       0
   247.8     .12       0  271.64     .08       0  306.11    .016       0
  340.58     .12       0
Bank Sta=228.5,247.8
XS Rating Curve= 0 ,0
Exp/Cntr=0.3,0.1

Type RM Length L Ch R = 1 ,1193.8  ,447.9,450.2,452.5
XS GIS Cut Line= 2
     1776310.494      353136.133     1776686.916      353513.965
#Sta/Elev= 30
       0  888.35       8     892    11.9  892.75    23.9   892.9    31.8  893.82
    67.7  892.88    87.6  893.36  140.49892.6849   155.2  893.33   163.2  892.86
   177.2  885.22   179.1   884.3   183.1  882.88   187.1  882.63     191  882.81
     195  884.07  199.04886.5566     203   888.2   234.8  890.35   250.8  887.63
  265.56888.8117  307.26888.4998   342.3  889.35     406  893.66   413.9   894.5
   425.9   897.3   457.7   908.5   477.6  917.98   497.5  928.95   533.3  950.26
#Mann= 7 ,-1 , 0
       0      .1       0  140.49     .12       0   177.2    .045       0
     195     .12       0  199.04     .08       0  265.56    .016       0
  307.26     .12       0
#XS Ineff= 2 , 0
          158.08  894.22  234.48          890.62
Permanent Ineff=
       F       F
Bank Sta=179.1,195
XS Rating Curve= 0 ,0
Exp/Cntr=0.3,0.1

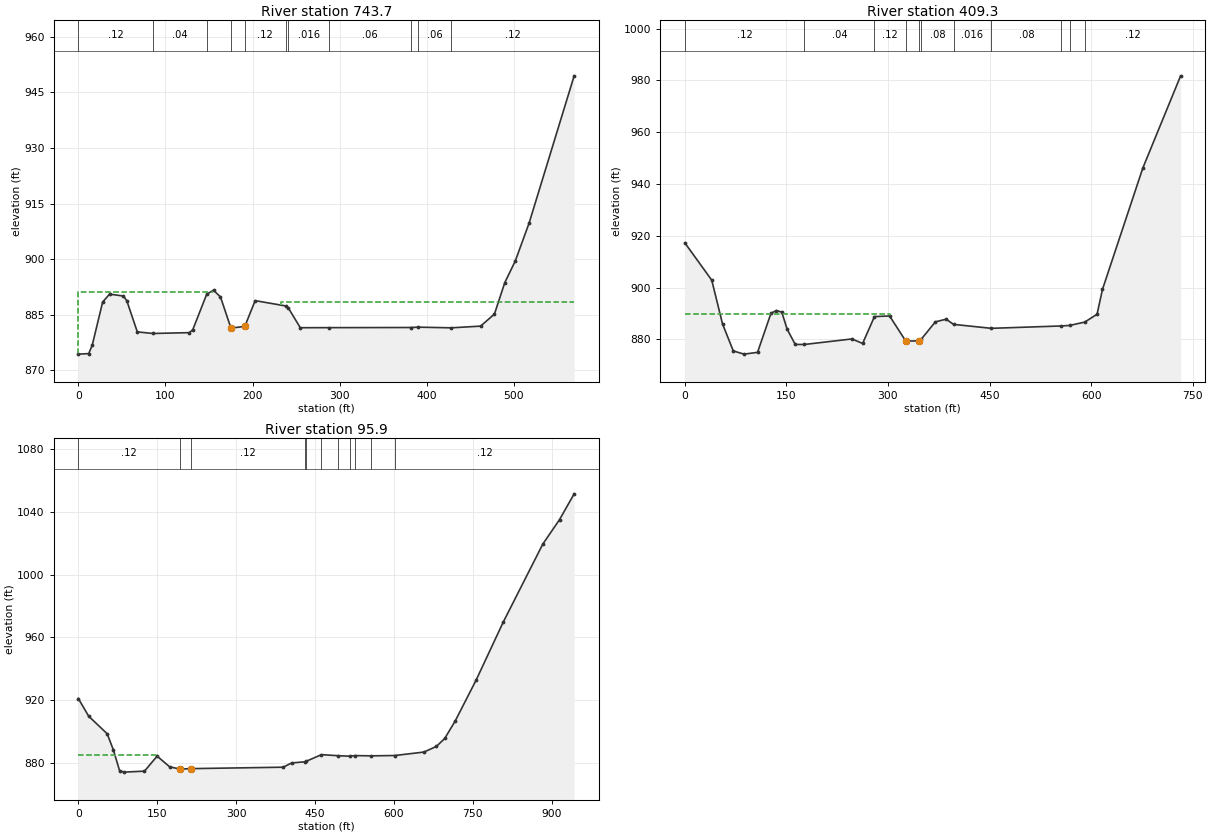
Type RM Length L Ch R = 1 ,743.7   ,331.2,334.4,337.5
XS GIS Cut Line= 2
     1775974.123       353405.23     1776332.749      353847.298
#Sta/Elev= 30
       0  874.36    11.9   874.5    15.9  876.71    27.9  888.41    35.8  890.56
    51.8  890.05    55.7  888.74    67.7  880.36   85.93879.9341   127.4  880.16
   131.4  880.96  147.45890.5809   155.2   891.6   163.2   889.8   175.2  881.38
   191.1  881.85     203   888.8  238.06887.3738  241.21 886.778   254.8  881.49
   288.1  881.51  381.87881.5483  390.19881.6416  428.22881.4616   461.8  881.92
   477.7  885.18   489.6  893.69   501.6   899.5   517.5  909.76   569.2   949.5
#Mann= 11 ,-1 , 0
       0     .12       0   85.93     .04       0  147.45     .12       0
   175.2    .045       0   191.1     .12       0  238.06     .08       0
  241.21    .016       0   288.1     .06       0  381.87     .12       0
  390.19     .06       0  428.22     .12       0
#XS Ineff= 2 , 0
          154.55  891.25  232.13          888.32
Permanent Ineff=
       F       F
Bank Sta=175.2,191.1
XS Rating Curve= 0 ,0
Exp/Cntr=0.3,0.1

Type RM Length L Ch R = 1 ,409.3   ,292.4,313.4,334.4
XS GIS Cut Line= 2
     1775655.129      353468.514     1776033.601       354095.25
#Sta/Elev= 30
       0  917.28    39.8  902.86    55.7  885.97    71.6  875.53    87.5   874.3
   107.4  874.98   127.3   890.1   135.3  891.12   143.2  890.52   151.2  883.88
   163.1  878.03  176.56878.0274   246.7  880.16   262.6  878.43  280.07888.7889
   302.4  889.04   326.3  879.34   346.2  879.42  349.07880.0299     370  886.76
     386  887.79  396.84885.7868  452.58884.2635  556.09885.1771  568.26885.3729
   590.6886.6675   608.8   889.7   616.8   899.3   676.4  946.17   732.2  981.75
#Mann= 11 ,-1 , 0
       0     .12       0  176.56     .04       0  280.07     .12       0
   326.3    .045       0   346.2     .12       0  349.07     .08       0
  396.84    .016       0  452.58     .08       0  556.09     .06       0
  568.26     .08       0   590.6     .12       0
#XS Ineff= 2 , 0
          302.45   889.8
Permanent Ineff=
       F       F
Bank Sta=326.3,346.2
XS Rating Curve= 0 ,0
Exp/Cntr=0.3,0.1

Type RM Length L Ch R = 1 ,95.9    ,82.1,95.9,109.6
XS GIS Cut Line= 4
     1775583.949      353480.667     1775618.671      353584.833
     1775439.851         354064.     1775452.004       354385.18
#Sta/Elev= 30
       0  921.06    19.6  909.82    54.9  898.58    66.7  888.22    78.4  875.11
    86.3  874.14   125.8  874.77   149.8  884.34   173.7   877.5   193.7  876.07
   213.3  876.36   389.5  877.28   405.5  879.98  430.71880.7151  432.51880.9459
  462.23885.2713  493.76884.6101  516.98884.2795  525.29884.6747  556.81884.5146
  601.45884.7203     657  886.92   680.8  890.52   696.6  895.59   716.5  906.71
   756.2  932.72   807.7  969.64   883.1 1019.49   914.9 1035.08   942.7 1051.51
#Mann= 11 ,-1 , 0
       0     .12       0   193.7    .045       0   213.3     .12       0
  430.71     .08       0  432.51     .12       0  462.23     .08       0
  493.76    .016       0  516.98     .08       0  525.29    .016       0
  556.81     .06       0  601.45     .12       0
#XS Ineff= 2 , 0
           150.7  884.79
Permanent Ineff=
       F       F
Bank Sta=193.7,213.3
XS Rating Curve= 0 ,0
Exp/Cntr=0.3,0.1
LCMann Table=0

Chan Stop Cuts=-1
Use User Specified Reach Order=0
Composite Channel Slope=5